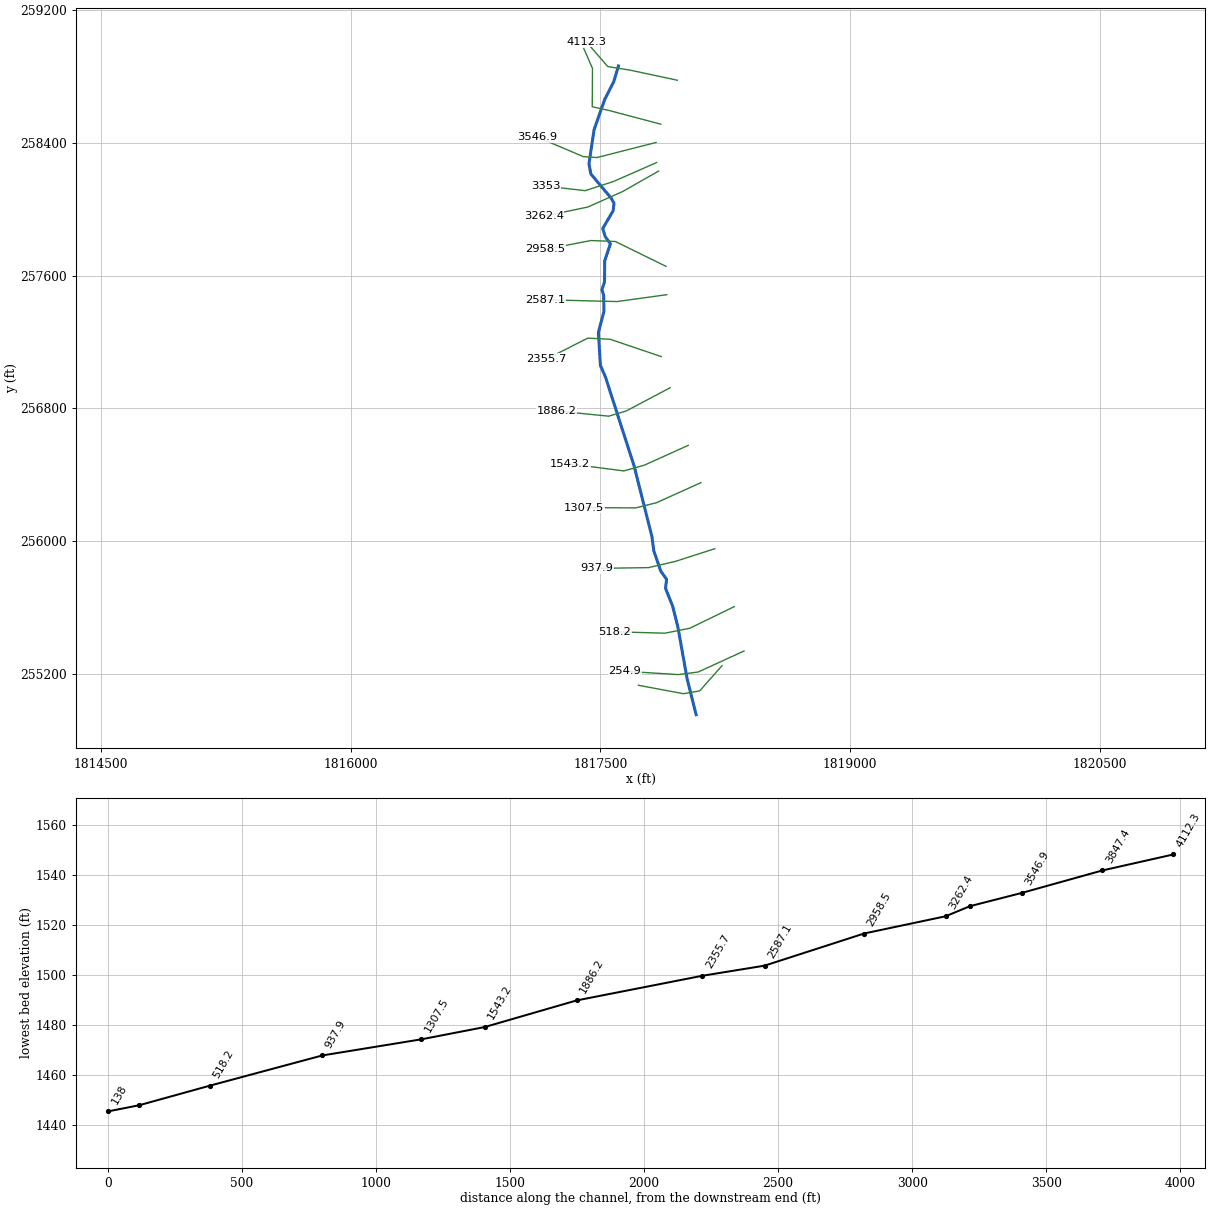
--- TmBaileyBr.prj (project) ---

Proj Title=TmBaileyBr
Current Plan=p01
Default Exp/Contr=0,0
English Units
Geom File=g01
Flow File=f01
Plan File=p01
BEGIN DESCRIPTION:
END DESCRIPTION:
DSS Export Rating Curves= 0
DSS Export Rating Curve Sorted= 0
DSS Export Volume Flow Curves= 0
DXF OffsetX= 0
DXF OffsetY= 0
DXF ScaleX= 0
DXF ScaleY= 0

--- TmBaileyBr.p01 (plan) ---

Plan Title=Floodplain
Program Version=4.00
Geom File=g01
Flow File=f01
K Sum by GR=0
Std Step Tol=0.01
Critical Tol=0.01
Num of Std Step Trials=20
Max Error Tol=0.3
Flow Tol Ratio=0.001
Split Flow NTrial=30
Split Flow Tol=0.02
Split Flow Ratio=0.02
Log Output Level=0
Friction Slope Method=1
Unsteady Friction Slope Method=2
Unsteady Bridges Friction Slope Method=1
Global Log Level=0
CheckData=False
Run HTab=0
Run UNet=0
Run PostProcess=0
UNET Theta=0
UNET Theta Warmup=0
UNET ZTol=0
UNET ZSATol=0
UNET MxIter=0
UNET MaxInSteps=0
UNET DtIC=0
UNET DtMin=0
UNET MaxCRTS=0
UNET WFStab=0
UNET SFStab=0
UNET WFX=0
UNET SFX=0
UNET DSS MLevel=0
UNET DZMax Abort=0
UNET Convert EG Bridges=0
UNET Use Existing IB Tables=0
UNET Froude Limit=0
UNET Froude Power=0
Write IC File=0
Echo Input=False
Echo Output=False
Write Detailed=0

--- TmBaileyBr.f01 (steady flow) ---

Flow Title=NFF Regression Equation
Program Version=4.00
Number of Profiles=1
Profile Names=P100yr
River Rch & RM=TmBaileyBr,Main      ,4112.3
540.5416
River Rch & RM=TmBaileyBr,Main      ,4112.3
341.5850
River Rch & RM=TmBaileyBr,Main      ,3847.4
542.0789
River Rch & RM=TmBaileyBr,Main      ,3847.4
344.2818
River Rch & RM=TmBaileyBr,Main      ,3546.9
674.4835
River Rch & RM=TmBaileyBr,Main      ,3546.9
442.2665
River Rch & RM=TmBaileyBr,Main      ,2958.5
702.9857
River Rch & RM=TmBaileyBr,Main      ,2958.5
464.3931
River Rch & RM=TmBaileyBr,Main      ,2355.7
743.1506
River Rch & RM=TmBaileyBr,Main      ,2355.7
495.7525
River Rch & RM=TmBaileyBr,Main      ,254.9
795.1314
River Rch & RM=TmBaileyBr,Main      ,254.9
535.7979
Boundary for River Rch & Prof#=TmBaileyBr,Main      ,1
Up Type=0
Dn Type=3
Dn Slope=0.026849

--- TmBaileyBr.g01 (geometry) ---

Geom Title=USGS 10m DEM
Program Version=4.00

River Reach=TmBaileyBr      ,Main
Reach XY= 30
     1817608.522      258860.426      1817580.69      258766.852
      1817525.96      258659.499     1817462.163      258477.494
     1817431.321      258271.086     1817442.961      258210.768
     1817564.854      258065.771     1817581.589      258035.103
     1817576.737      257989.515     1817514.206      257883.258
     1817528.865      257834.476     1817560.056      257790.809
     1817525.985      257688.598     1817524.855      257560.957
     1817509.275      257514.302     1817519.895      257480.923
     1817521.414      257383.835     1817488.034      257257.893
     1817500.172      257059.137     1817530.516      256989.346
     1817703.055      256452.467     1817809.585      256029.227
     1817820.622      255944.771     1817862.479      255821.894
     1817897.682      255772.539     1817891.286      255717.357
      1817933.87      255610.786     1817965.061      255487.461
     1818020.725      255174.589     1818075.048      254957.799

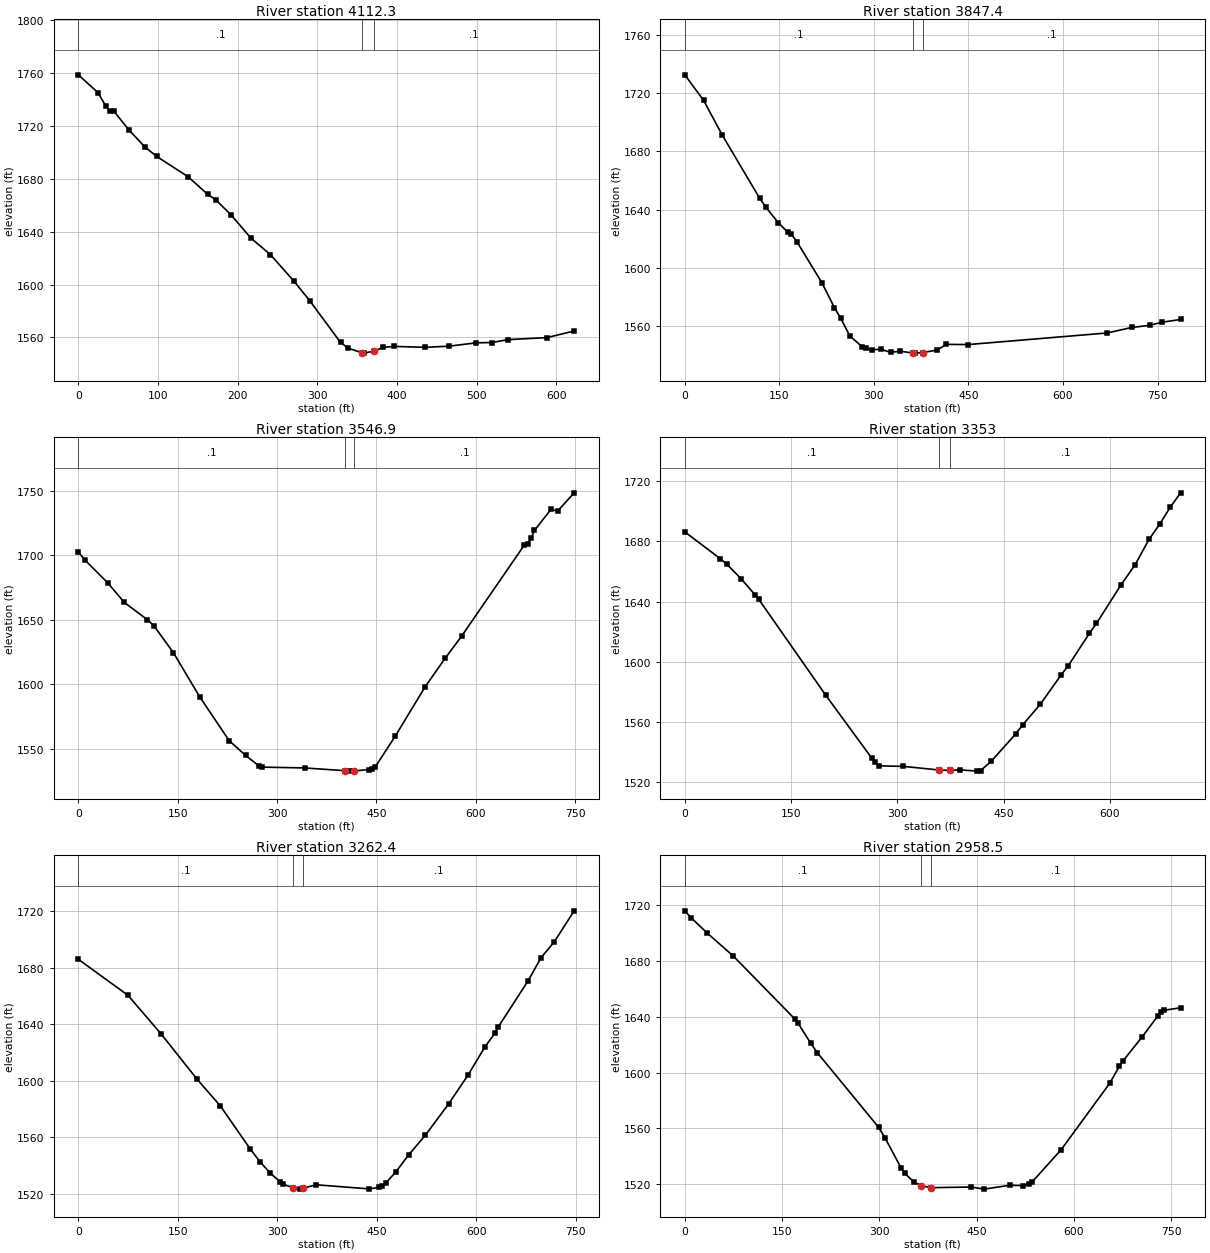
Type RM Length L Ch R = 1 ,4112.3  ,266.1,264.9,263.7
XS GIS Cut Line= 4
      1817962.47      258774.895     1817683.156      258834.628
      1817544.53      258857.261     1817415.805      259005.789
#Sta/Elev= 30
       0 1758.79    24.6 1745.38    34.5 1735.12    39.4 1731.42    44.3 1731.48
      64 1716.73    83.7 1704.13    98.5 1696.96   137.9  1681.6   162.5 1668.27
   172.4 1664.28   192.1 1652.55   216.7 1635.18   241.3 1622.62   270.9 1602.45
   290.5 1587.86   329.2 1556.21   338.9 1551.85   356.6 1548.25   358.3 1548.09
   371.6 1549.57   382.5 1552.46     397 1553.18   435.9 1552.47   465.4 1553.36
   499.8 1555.88   519.4 1556.12   539.1 1558.29   588.2 1559.84   622.6 1564.85
#Mann= 3 , 0 , 0
       0      .1       0   356.6    .045       0   371.6      .1       0
Bank Sta=356.6,371.6
XS Rating Curve= 0 ,0
Exp/Cntr=0.3,0.1

Type RM Length L Ch R = 1 ,3847.4  ,297.2,300.6,303.9
XS GIS Cut Line= 5
     1817862.804      258510.695     1817547.359      258594.154
     1817451.169      258615.372     1817452.584      258845.945
     1817400.245      258966.182
#Sta/Elev= 30
       0 1732.38    29.7 1714.95    59.3  1691.2   118.6  1647.9   128.5 1641.76
   148.3 1631.05   163.2 1624.56   168.1 1623.63     178 1617.92   217.5  1589.9
   237.3 1572.92   247.2 1565.66     262 1553.32   281.8 1545.94   286.8 1544.96
   296.6 1544.04   311.5 1544.31   326.3 1542.22   341.1 1543.02   362.6 1541.76
   365.7  1541.7   377.6 1542.12   400.2 1543.77     415 1547.71   449.3 1547.56
     670 1555.51   708.8 1559.26   737.9 1560.78   757.4 1562.91   786.5 1564.76
#Mann= 3 , 0 , 0
       0      .1       0   362.6    .045       0   377.6      .1       0
Bank Sta=362.6,377.6
XS Rating Curve= 0 ,0
Exp/Cntr=0.3,0.1

Type RM Length L Ch R = 1 ,3546.9  ,185.4,193.9,202.4
XS GIS Cut Line= 4
     1817834.513       258400.36      1817479.46      258309.829
     1817397.416      258315.487     1817121.351      258432.775
#Sta/Elev= 30
       0 1702.77     9.9 1696.43    44.6 1678.59    69.3 1663.59     104 1650.22
   113.9 1645.57   143.6 1624.52   183.2 1590.39   227.8 1556.33   252.5  1544.9
   272.3 1536.96   277.3 1535.84   341.7  1535.2   401.9 1533.08     410 1532.73
   416.9 1532.88     439 1533.94   443.8  1534.5   448.6 1536.22   478.6 1559.95
   523.6 1598.11   553.6 1620.09   578.6 1637.33   673.6 1708.21   678.6 1708.89
   683.6 1713.35   688.6 1719.33   713.6 1735.66   723.6 1734.38   748.6 1748.51
#Mann= 3 , 0 , 0
       0      .1       0   401.9    .045       0   416.9      .1       0
Bank Sta=401.9,416.9
XS Rating Curve= 0 ,0
Exp/Cntr=0.3,0.1

Type RM Length L Ch R = 1 ,3353    ,88.1,90.6,93.1
XS GIS Cut Line= 4
     1817837.829      258279.822      1817578.27      258165.498
      1817408.19      258110.506     1817172.205       258138.02
#Sta/Elev= 30
       0 1686.31    49.8 1668.64    59.7  1664.7    79.6 1655.14    99.5 1644.35
   104.5 1641.47     199 1577.82   263.7 1536.24   268.7 1533.21   273.7 1530.94
   308.4 1530.57   359.3 1528.16   374.3 1527.89   387.9 1528.28   412.7 1527.42
   417.7 1527.83   432.6 1533.96   467.3  1552.2   477.2 1558.23     502 1571.88
   531.7 1591.58   541.6 1597.56   571.3 1619.02   581.2 1625.53   615.8 1651.12
   635.6 1664.39   655.4 1681.34   670.3 1691.37   685.1 1702.56     700 1712.27
#Mann= 3 , 0 , 0
       0      .1       0   359.3    .045       0   374.3      .1       0
Bank Sta=359.3,374.3
XS Rating Curve= 0 ,0
Exp/Cntr=0.3,0.1

Type RM Length L Ch R = 1 ,3262.4  ,314.1,303.9,288.9
XS GIS Cut Line= 4
     1817850.221      258228.552      1817633.63      258105.298
     1817424.219       258011.96     1817160.629      257956.848
#Sta/Elev= 30
       0 1686.07    74.8 1660.63   124.6 1633.38   179.4 1601.03   214.3  1582.2
   259.2 1551.85   274.1 1542.68   289.1 1534.94     304 1528.67     309 1526.91
   323.4 1524.41   333.9  1523.4   338.4 1524.03   358.9 1526.46   438.6 1523.58
   453.6 1524.64   458.5 1525.46   463.5  1527.6   478.5  1535.4   498.4 1547.73
   523.4 1561.57   558.3 1583.61   588.2 1604.47   613.1 1623.97   628.1 1633.66
   633.1 1638.05     678 1670.58   697.9 1687.24   717.8 1698.44   747.8 1720.39
#Mann= 3 , 0 , 0
       0      .1       0   323.4    .045       0   338.4      .1       0
Bank Sta=323.4,338.4
XS Rating Curve= 0 ,0
Exp/Cntr=0.3,0.1

Type RM Length L Ch R = 1 ,2958.5  ,371,371.4,376.7
XS GIS Cut Line= 4
     1817893.907      257655.312     1817589.795      257804.834
     1817442.682      257810.492     1817169.198      257757.217
#Sta/Elev= 30
       0 1715.93      10 1710.87    34.9 1699.85    74.8 1683.54   169.4 1638.56
   174.4 1635.64   194.4 1620.92   204.3 1614.32     299 1560.78     309 1553.07
   333.9 1531.48   338.9 1527.96   353.6 1521.56     365 1518.88     380 1517.57
   441.9 1518.03   461.6 1516.52     501 1519.28   520.9 1519.08   530.9 1520.32
   535.9 1521.78   580.6 1544.87   655.3 1592.32   670.2 1604.55   675.2 1608.05
     705 1625.39   729.9 1640.77   734.9 1643.41   739.8 1644.73   764.7 1646.46
#Mann= 3 , 0 , 0
       0      .1       0     365    .045       0     380      .1       0
Bank Sta=365,380
XS Rating Curve= 0 ,0
Exp/Cntr=0.3,0.1

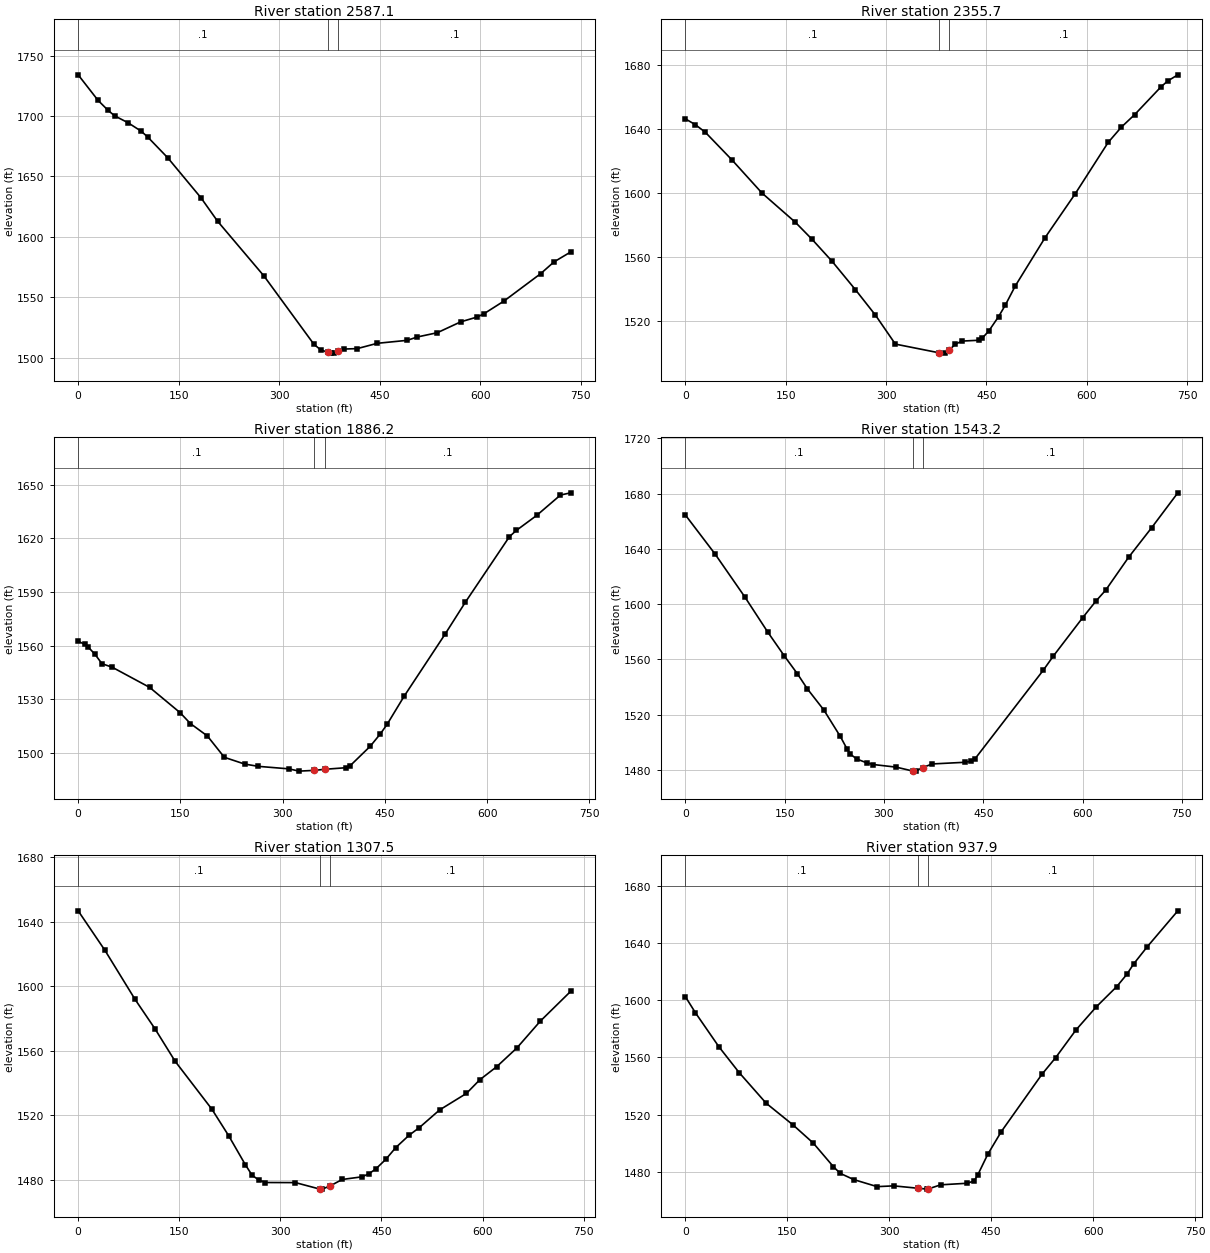
Type RM Length L Ch R = 1 ,2587.1  ,231.6,231.4,231.2
XS GIS Cut Line= 3
     1817899.148      257484.788      1817599.95      257443.432
     1817167.155      257454.244
#Sta/Elev= 30
       0  1734.2    29.7 1713.03    44.6  1704.8    54.5 1700.21    74.3 1694.55
    94.1  1687.5     104 1682.57   133.7 1665.47   183.2  1632.4     208 1612.98
   277.3 1567.56   351.8 1511.02   361.8 1506.44   372.8 1504.34   376.7 1503.68
   381.7 1503.86   387.8 1505.25   396.6 1507.06   416.5 1507.42   446.4 1511.82
   491.1 1514.28   506.1 1517.06   535.9 1520.58   570.8 1529.57   595.6 1533.62
   605.6 1536.31   635.4  1546.8   690.2  1569.5   710.1 1579.24     735 1587.47
#Mann= 3 , 0 , 0
       0      .1       0   372.8    .045       0   387.8      .1       0
Bank Sta=372.8,387.8
XS Rating Curve= 0 ,0
Exp/Cntr=0.3,0.1

Type RM Length L Ch R = 1 ,2355.7  ,461.7,469.5,477.3
XS GIS Cut Line= 4
     1817865.479      257112.445     1817558.675       257216.38
     1817424.293      257223.453     1817176.746      257097.557
#Sta/Elev= 30
       0 1646.12      15 1642.46    29.9 1637.72    69.8  1620.4   114.6 1599.73
   164.5 1581.45   189.4 1570.83   219.3 1557.11   254.2 1539.36   284.1 1523.48
     314  1505.3   379.6 1499.84   388.7 1499.66   394.6 1501.63   403.7 1505.26
   413.6 1507.19   438.6  1507.7   443.6 1508.92   453.5 1513.41   468.4 1522.55
   478.3 1529.63   493.2 1541.62   537.8 1571.86   582.5 1599.05   632.1 1631.38
   651.9 1640.95   671.8 1648.79   711.4 1666.25   721.3 1669.82   736.2 1673.61
#Mann= 3 , 0 , 0
       0      .1       0   379.6    .045       0   394.6      .1       0
Bank Sta=379.6,394.6
XS Rating Curve= 0 ,0
Exp/Cntr=0.3,0.1

Type RM Length L Ch R = 1 ,1886.2  ,343.3,343,342.6
XS GIS Cut Line= 4
     1817919.386      256924.982     1817654.865      256784.941
     1817550.188      256753.821     1817237.572      256784.941
#Sta/Elev= 30
       0 1562.44      10 1560.63      15 1559.08    24.9 1555.03    34.9 1549.88
    49.9 1547.92   104.8 1536.65   149.6 1522.48   164.6 1516.43   189.6 1509.46
   214.5 1497.52   244.4 1493.74   264.4 1492.47   309.2 1491.07   324.1  1489.8
   346.6 1490.22   361.6 1490.82   393.6 1491.73   398.6 1492.64   428.5 1503.68
   443.4 1510.62   453.4 1516.01   478.3 1531.68   538.2 1566.29   568.1 1584.24
   632.9 1620.97   642.9 1624.39   672.8  1632.8   707.7  1644.2   722.7 1645.44
#Mann= 3 , 0 , 0
       0      .1       0   346.6    .045       0   361.6      .1       0
Bank Sta=346.6,361.6
XS Rating Curve= 0 ,0
Exp/Cntr=0.3,0.1

Type RM Length L Ch R = 1 ,1543.2  ,236.4,235.8,235.1
XS GIS Cut Line= 4
     1818027.776      256578.281     1817764.562      256459.142
     1817641.267      256424.508     1817317.098      256466.068
#Sta/Elev= 30
       0 1664.57    44.8 1636.36    89.7 1605.35   124.5 1579.79   149.4 1562.63
   169.4 1549.54   184.3 1538.71   209.2 1523.42   234.1 1504.26   244.1 1495.37
   249.1 1491.52     259 1487.92     274 1485.17   283.9 1483.95   318.5 1482.06
   343.7 1479.22     348 1479.17   358.7 1481.77   372.7 1484.36   421.9 1485.56
   431.8 1486.32   436.8 1487.63   540.8  1552.3   555.6  1562.3   600.2 1590.25
     620 1602.14   634.9 1610.14   669.5 1633.92   704.2 1655.25   743.8 1680.54
#Mann= 3 , 0 , 0
       0      .1       0   343.7    .045       0   358.7      .1       0
Bank Sta=343.7,358.7
XS Rating Curve= 0 ,0
Exp/Cntr=0.3,0.1

Type RM Length L Ch R = 1 ,1307.5  ,370,369.6,369.3
XS GIS Cut Line= 4
     1818103.968      256354.016     1817837.342      256233.266
     1817712.532      256202.048     1817403.074       256203.56
#Sta/Elev= 30
       0 1646.73    39.7 1622.26    84.3 1591.93   114.1 1573.55   143.9 1553.49
   198.4 1523.81   223.2 1507.46     248 1489.46     258 1482.94   267.9 1479.93
   277.8 1478.38   322.4 1478.32   358.7 1474.29     362 1474.28   373.7 1476.23
   391.7 1480.26   421.4 1481.92   431.3 1483.79   441.3 1486.67   456.3 1492.66
   471.3 1500.04   491.2 1507.74   506.2 1512.39   536.2 1523.32   576.1 1533.58
     596 1542.07     621 1550.14     651 1561.78   685.9 1578.45   730.8 1596.84
#Mann= 3 , 0 , 0
       0      .1       0   358.7    .045       0   373.7      .1       0
Bank Sta=358.7,373.7
XS Rating Curve= 0 ,0
Exp/Cntr=0.3,0.1

Type RM Length L Ch R = 1 ,937.9   ,421.8,419.7,416.7
XS GIS Cut Line= 4
      1818187.49      255956.527     1817951.704      255880.494
     1817788.814      255842.666     1817479.244      255838.057
#Sta/Elev= 30
       0 1602.49    14.9 1591.16    49.6 1567.27    79.3 1549.28   118.9 1527.94
   158.6 1512.68   188.3 1500.03     218 1483.47   227.9 1478.88   247.7 1474.54
   282.2 1469.58   306.8 1470.12   341.8 1468.48     356 1467.84   356.8 1467.87
   375.6 1470.85     415 1471.95     425 1473.64     430 1477.51   444.9 1492.13
   464.9 1508.07   524.8  1548.2   544.8 1559.73   574.8 1579.17   604.7 1595.32
   634.7 1609.44   649.7 1618.08   659.6 1625.28   679.6  1637.3   724.6 1662.43
#Mann= 3 , 0 , 0
       0      .1       0   341.8    .045       0   356.8      .1       0
Bank Sta=341.8,356.8
XS Rating Curve= 0 ,0
Exp/Cntr=0.3,0.1

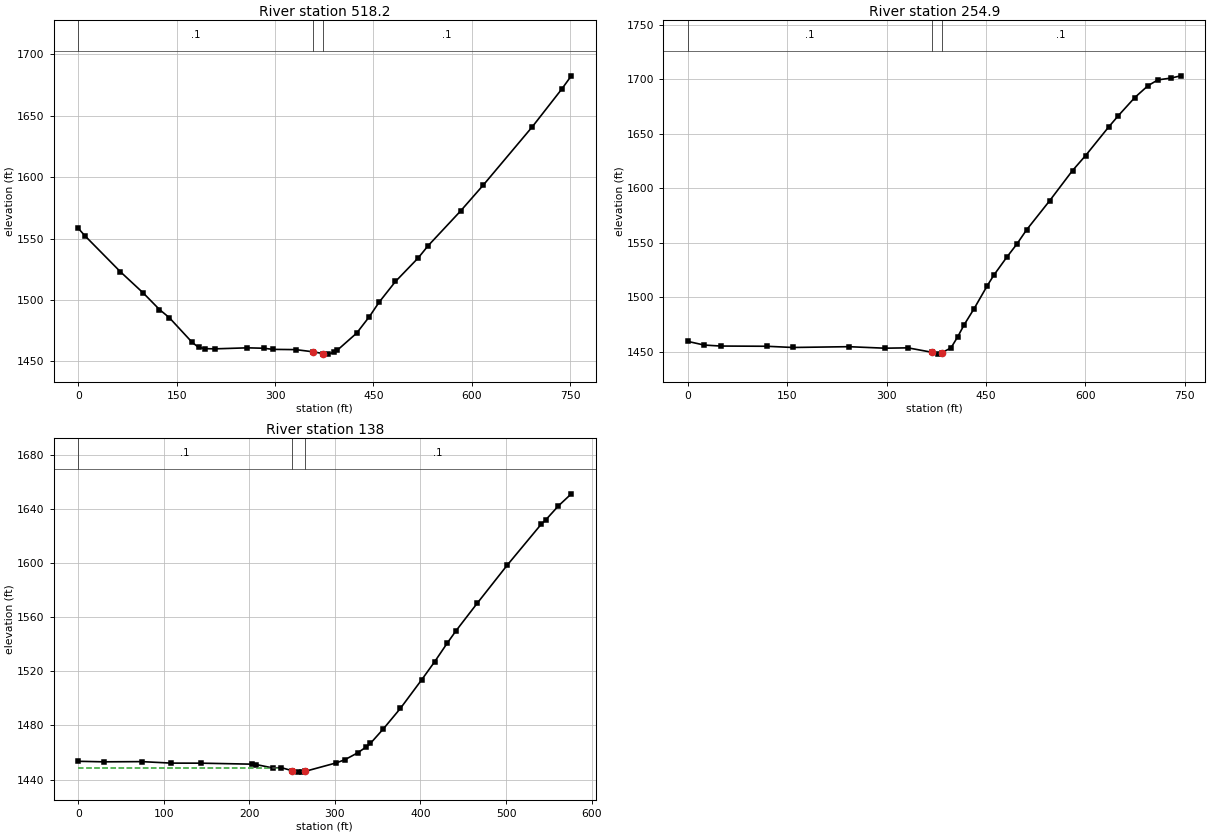
Type RM Length L Ch R = 1 ,518.2   ,264.8,263.3,261.8
XS GIS Cut Line= 4
     1818304.144      255608.033     1818036.794      255477.895
     1817888.266      255448.189     1817585.552      255456.676
#Sta/Elev= 30
       0 1558.38     9.9 1552.41    64.4 1522.86    99.1 1505.62   123.9 1492.11
   138.8 1485.53   173.4 1465.53   183.4 1461.27   193.3 1460.24   208.1 1460.07
   257.7  1460.9   282.5 1460.57   297.3 1459.64   331.6 1459.44   357.8 1457.68
   372.8 1456.26   380.4 1455.77   390.2 1457.31   395.1 1459.04   424.4 1472.88
   443.9  1486.4   458.7 1498.12   483.6 1514.98   518.3 1534.22   533.2 1544.03
   582.8 1572.42   617.6 1593.66   692.1 1641.04   736.8 1671.64   751.6 1682.59
#Mann= 3 , 0 , 0
       0      .1       0   357.8    .045       0   372.8      .1       0
Bank Sta=357.8,372.8
XS Rating Curve= 0 ,0
Exp/Cntr=0.3,0.1

Type RM Length L Ch R = 1 ,254.9   ,116,116.9,117.8
XS GIS Cut Line= 4
     1818362.559       255340.86     1818087.718      255214.788
     1817968.895      255199.228     1817647.792      255219.031
#Sta/Elev= 30
       0 1459.66    24.8 1456.29    49.6 1455.37     119 1455.17   158.6 1454.06
   242.9 1454.78   297.4  1453.4   332.3 1453.72     368 1449.72   377.3 1447.96
     383 1449.14   397.2 1453.63   407.2 1463.61   417.2 1474.93   432.1 1489.58
   451.9 1510.55   461.8 1520.23   481.6 1536.92   496.5 1548.68   511.3 1561.84
     546 1588.43   580.6  1616.2   600.4 1629.97     635 1656.01   649.9  1666.6
   674.6 1683.13   694.4 1693.92   709.3 1699.27   729.1 1700.94   743.9    1703
#Mann= 3 , 0 , 0
       0      .1       0     368    .045       0     383      .1       0
Bank Sta=368,383
XS Rating Curve= 0 ,0
Exp/Cntr=0.3,0.1

Type RM Length L Ch R = 1 ,138     ,135.1,138,140.9
XS GIS Cut Line= 4
     1818230.686      255252.918      1818096.25      255101.043
     1817998.893      255084.112     1817728.914      255134.722
#Sta/Elev= 30
       0 1453.51    29.7 1453.11    74.2 1453.26   108.8 1452.16   143.5 1452.12
   202.8 1451.38   207.8 1451.12   227.5 1448.56   237.4 1448.81     250 1446.55
   257.2 1445.49   262.1 1445.59     265 1446.03   301.6 1452.33   311.6 1454.67
   326.6 1459.74   336.6 1464.14   341.6 1466.81   356.6 1477.46   376.6 1492.68
   401.5 1513.87   416.5 1527.08   431.5 1541.11   441.5    1550   466.4 1570.47
   501.4 1598.58   541.4 1629.08   546.4 1632.05   561.3 1642.47   576.3 1651.34
#Mann= 3 , 0 , 0
       0      .1       0     250    .045       0     265      .1       0
#XS Ineff= 2 , 0
          235.68 1448.89
Permanent Ineff=
       F       F
Bank Sta=250,265
XS Rating Curve= 0 ,0
Exp/Cntr=0.3,0.1

Chan Stop Cuts=-1
Use User Specified Reach Order=0